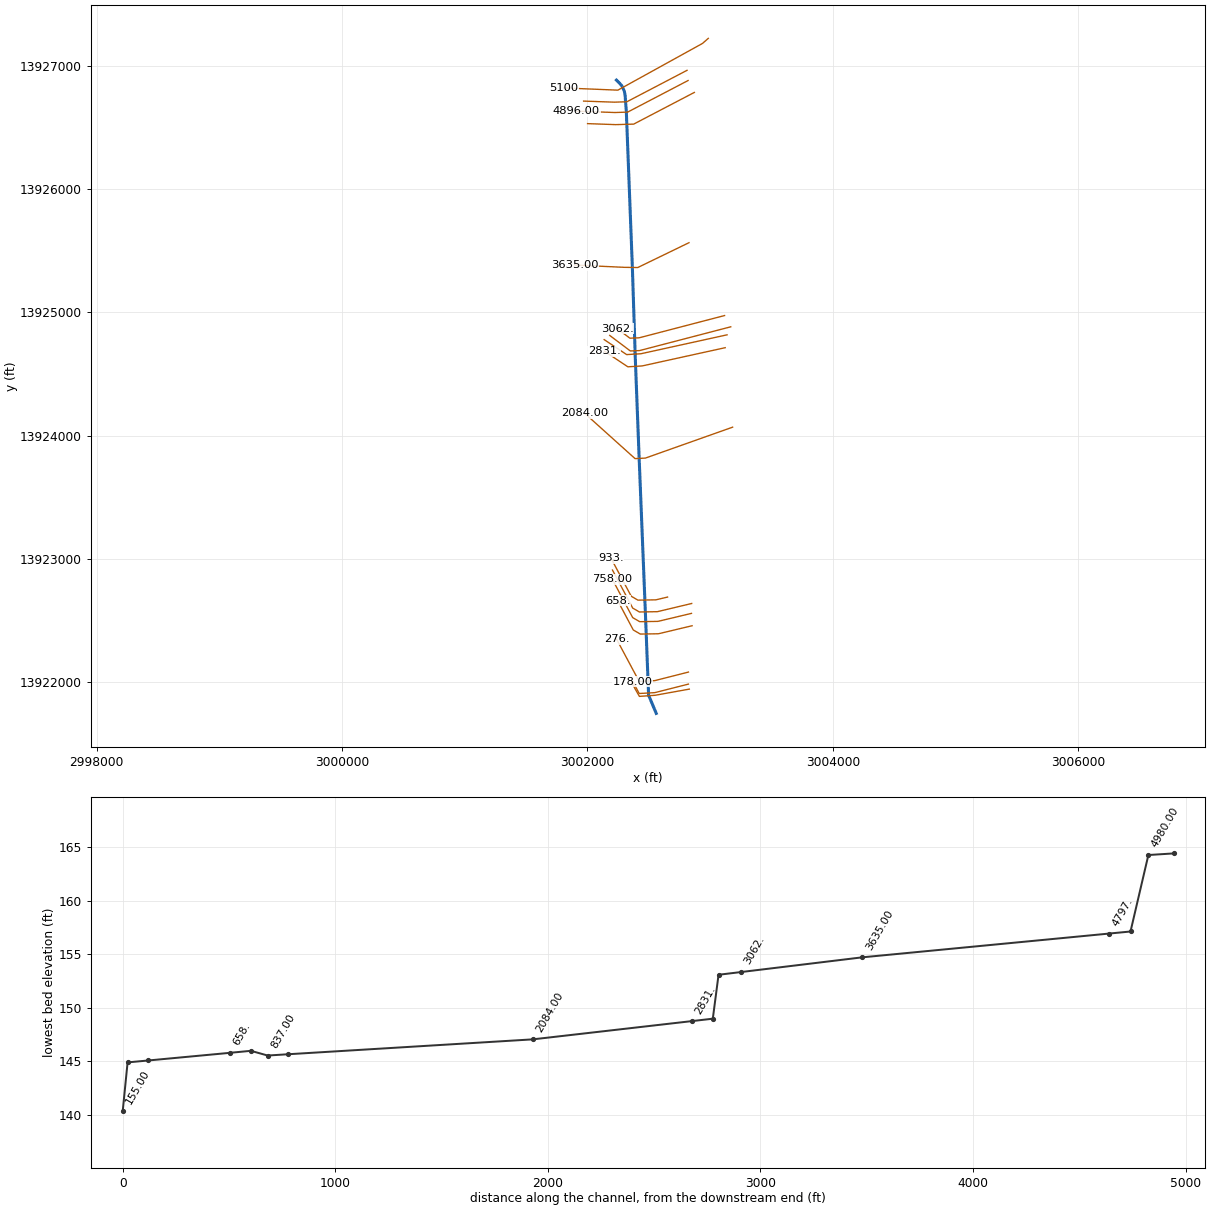
--- K159-01-00.prj (project) ---

Proj Title=K159-01-00
Current Plan=p02
Default Exp/Contr=.3,.1
English Units
Geom File=g01
Flow File=f02
Flow File=f01
Flow File=f04
Plan File=p01
Plan File=p04
Plan File=p02
Y Axis Title=Elevation
X Axis Title(PF)=Main Channel Distance
X Axis Title(XS)=Station
BEGIN DESCRIPTION:
Cypress Creek  Watershed
Cypress Creek Channel D
HCFCD Unit K159-01-00
Flood Hazard Model
10, 2, 1, 0.2%
Filename K159-01-00
Prepared by:  Halff Associates  DATE:  03-26-04
Reviewed by:  _________  DATE:  __________________
STATUS (Final)
END DESCRIPTION:
DSS File=dss
DSS Export Rating Curves= 0
DSS Export Rating Curve Sorted= 0
DSS Export Volume Flow Curves= 0
DXF OffsetX= 0
DXF OffsetY= 0
DXF ScaleX= 1
DXF ScaleY= 10

--- K159-01-00.p02 (plan) ---

Plan Title=Floodway
Version=Version 3.0.1  Mar 2001
Short Identifier=Floodway0607
Geom File=g01
Flow File=f02
Subcritical Flow
K Sum by GR= 0
Std Step Tol= 0.01
Critical Tol= 0.01
Num of Std Step Trials= 20
Max Error Tol= 0.3
Flow Tol Ratio= 0.001
Split Flow NTrial= 30
Split Flow Tol= 0.02
Split Flow Ratio= 0.02
Log Output Level= 0
Friction Slope Method= 1
Unsteady Friction Slope Method= 2
Parabolic Critical Depth
Global Vel Dist= 0 , 0 , 0
Global Log Level= 0
CheckData=True
Encroach Param=-1 ,0,0, 2
Encroach River=K159-01-00
Encroach Reach=Reach - 1
Encroach Node=5100
       1  4977.4  5020.5
Encroach Node=4980.00
       1  4977.4 5922.35
Encroach Node=4938.00
       1  4977.4  5020.5
Encroach Node=4896.00
       1  4977.4  5020.5
Encroach Node=4797.
       1    4944 5048.16
Encroach Node=3635.00
       1  4959.3  5038.2
Encroach Node=3062.
       1 4966.33  5038.8
Encroach Node=2958.00
       1  4967.6  5032.4
Encroach Node=2945.00
       1  4967.6  5032.4
Encroach Node=2931.00
       1  4968.3  5032.3
Encroach Node=2831.
       1 4967.56 5032.41
Encroach Node=2084.00
       1    4962  5033.2
Encroach Node=933.
       1    4960 5039.89
Encroach Node=837.00
       1  4958.7  5042.9
Encroach Node=798.00
       1  4958.7  5042.9
Encroach Node=758.00
       1  4958.7  5042.9
Encroach Node=658.
       1  4959.7 5039.81
Encroach Node=276.
       1 4961.86 5038.66
Encroach Node=178.00
       1  4962.5  5037.8
Encroach Node=167.00
       1  4962.5  5037.8
Encroach Node=155.00
       1  4951.7    5050
Encroach Reach=K159-01-00_0002
Encroach Node=5100
       1  4977.4  5020.5
Encroach Node=4980.00
       1  4977.4 5922.35
Encroach Node=4938.00
       1  4977.4  5020.5
Encroach Node=4896.00
       1  4977.4  5020.5
Encroach Node=4797.
       1    4944 5048.16
Encroach Node=3635.00
       1  4959.3  5038.2
Encroach Node=3062.
       1 4966.33  5038.8
Encroach Node=2958.00
       1  4967.6  5032.4
Encroach Node=2945.00
       1  4967.6  5032.4
Encroach Node=2931.00
       1  4968.3  5032.3
Encroach Node=2831.
       1 4967.56 5032.41
Encroach Node=2084.00
       1    4962  5033.2
Encroach Node=933.
       1    4960 5039.89
Encroach Node=837.00
       1  4958.7  5042.9
Encroach Node=798.00
       1  4958.7  5042.9
Encroach Node=758.00
       1  4958.7  5042.9
Encroach Node=658.
       1  4959.7 5039.81
Encroach Node=276.
       1 4961.86 5038.66
Encroach Node=178.00
       1  4962.5  5037.8
Encroach Node=167.00
       1  4962.5  5037.8
Encroach Node=155.00
       1  4951.7    5050
Computation Interval=1HOUR
Output Interval=1HOUR
Run HTab= 0
Run UNet= 0
Run PostProcess= 0
UNET Theta= 1
UNET ZTol= 0.02
UNET ZSATol= 0.1
UNET MxIter= 20
UNET MaxInSteps= 20
UNET DtIC= 0
UNET DtMin= 0
UNET MaxCRTS= 20
UNET WFStab= 2
UNET SFStab= 1
UNET WFX= 1
UNET SFX= 1
UNET Convert EG Bridges=-1
UNET Use Existing IB Tables=-1
Instantaneous Interval=1HOUR
Write IC File= 0
Write Velocity= 0
Write Detailed= 0

--- K159-01-00.p01 (plan) ---

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Plan Title=FEMA Effective June 2007
Short Identifier=FEMAeff0607
Geom File=g01
Flow File=f01
DSS File=dss
IC Time=0

--- K159-01-00.p04 (plan) ---

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Plan Title=Storage Routing
Short Identifier=Store_Rout
Geom File=g01
Flow File=f04
Encroach Param=-1 ,0,0, 0

--- K159-01-00.f02 (steady flow) ---

Flow Title=Floodway
Version=Version 3.0.1  Mar 2001
Number of Profiles= 2
Profile Names=1PCT_100yr, 1PCTFloodway_100yrFW
River Rch & RM=K159-01-00,K159-01-00_0002,5100
     700     700
River Rch & RM=K159-01-00,K159-01-00_0002,3635.00
     720     720
River Rch & RM=K159-01-00,K159-01-00_0002,2958.00
     740     740
River Rch & RM=K159-01-00,K159-01-00_0002,2084.00
     780     780
River Rch & RM=K159-01-00,K159-01-00_0002,758.00
     800     800
Boundary for River Rch & Prof#=K159-01-00,K159-01-00_0002, 1
Up Type= 0
Dn Type= 3
Dn Slope=.00099
Boundary for River Rch & Prof#=K159-01-00,K159-01-00_0002, 2
Up Type= 0
Dn Type= 3
Dn Slope=.00099
DSS Import GetInterval= 0
DSS Import GetPeak= 0
DSS Import FillOption= 0

--- K159-01-00.f01 (steady flow) ---

Flow Title=FEMA Effective June 2007
Version=Version 3.0.1  Mar 2001
Number of Profiles= 4
Profile Names=10PCT_10yr, 2PCT_50yr, 1PCT_100yr, 0.2PCT_500yr
River Rch & RM=K159-01-00,K159-01-00_0002,5100*
     370     580     700    1030
River Rch & RM=K159-01-00,K159-01-00_0002,3635.00
     380     590     720    1070
River Rch & RM=K159-01-00,K159-01-00_0002,2958.00
     390     610     740    1120
River Rch & RM=K159-01-00,K159-01-00_0002,2084.00
     410     640     780    1210
River Rch & RM=K159-01-00,K159-01-00_0002,758.00
     420     650     800    1250
Boundary for River Rch & Prof#=K159-01-00,K159-01-00_0002, 1
Up Type= 0
Dn Type= 3
Dn Slope=.00099
Boundary for River Rch & Prof#=K159-01-00,K159-01-00_0002, 2
Up Type= 0
Dn Type= 3
Dn Slope=.00099
Boundary for River Rch & Prof#=K159-01-00,K159-01-00_0002, 3
Up Type= 0
Dn Type= 3
Dn Slope=.00099
Boundary for River Rch & Prof#=K159-01-00,K159-01-00_0002, 4
Up Type= 0
Dn Type= 3
Dn Slope=.00099
DSS Import GetInterval= 0
DSS Import GetPeak= 0
DSS Import FillOption= 0

--- K159-01-00.f04 (steady flow) ---

Flow Title=Storage Routing
Version=Version 3.0.1  Mar 2001
Number of Profiles= 7
Profile Names=0.25*10% flood, 0.50*10%flood, 10% flood, 2% flood, 1% flood, 0.2%flood, 1.25*0.2% flood
River Rch & RM=K159-01-00,K159-01-00_0002,5100
      90     180     360     480     540     670     840
Boundary for River Rch & Prof#=K159-01-00,K159-01-00_0002, 1
Up Type= 0
Dn Type= 3
Dn Slope=.00099
Boundary for River Rch & Prof#=K159-01-00,K159-01-00_0002, 2
Up Type= 0
Dn Type= 3
Dn Slope=.00099
Boundary for River Rch & Prof#=K159-01-00,K159-01-00_0002, 3
Up Type= 0
Dn Type= 3
Dn Slope=.00099
Boundary for River Rch & Prof#=K159-01-00,K159-01-00_0002, 4
Up Type= 0
Dn Type= 3
Dn Slope=.00099
Boundary for River Rch & Prof#=K159-01-00,K159-01-00_0002, 5
Up Type= 0
Dn Type= 3
Dn Slope=.00099
Boundary for River Rch & Prof#=K159-01-00,K159-01-00_0002, 6
Up Type= 0
Dn Type= 3
Dn Slope=.00099
Boundary for River Rch & Prof#=K159-01-00,K159-01-00_0002, 7
Up Type= 0
Dn Type= 3
Dn Slope=.00099
DSS Import GetInterval= 0
DSS Import GetPeak= 0
DSS Import FillOption= 0

--- K159-01-00.g01 (geometry) ---

Geom Title=K159-01-00 June 2007
Version=Version 3.0.1  Mar 2001

River Reach=K159-01-00      ,K159-01-00_0002
Reach XY= 17
       3002235.9     13926886.28     3002257.689     13926864.49
     3002279.479     13926840.28     3002300.058      13926796.7
     3002307.322     13926759.17      3002309.69      13926716.6
      3002311.17       13926701.      3002316.43     13926635.73
      3002365.97     13925362.52      3002388.01     13924681.56
      3002388.08     13924671.25      3002421.39     13923811.01
      3002471.65     13922570.32      3002496.75      13921930.9
        3002498.     13921907.26      3002497.27      13921895.8
       3002560.5       13921746.

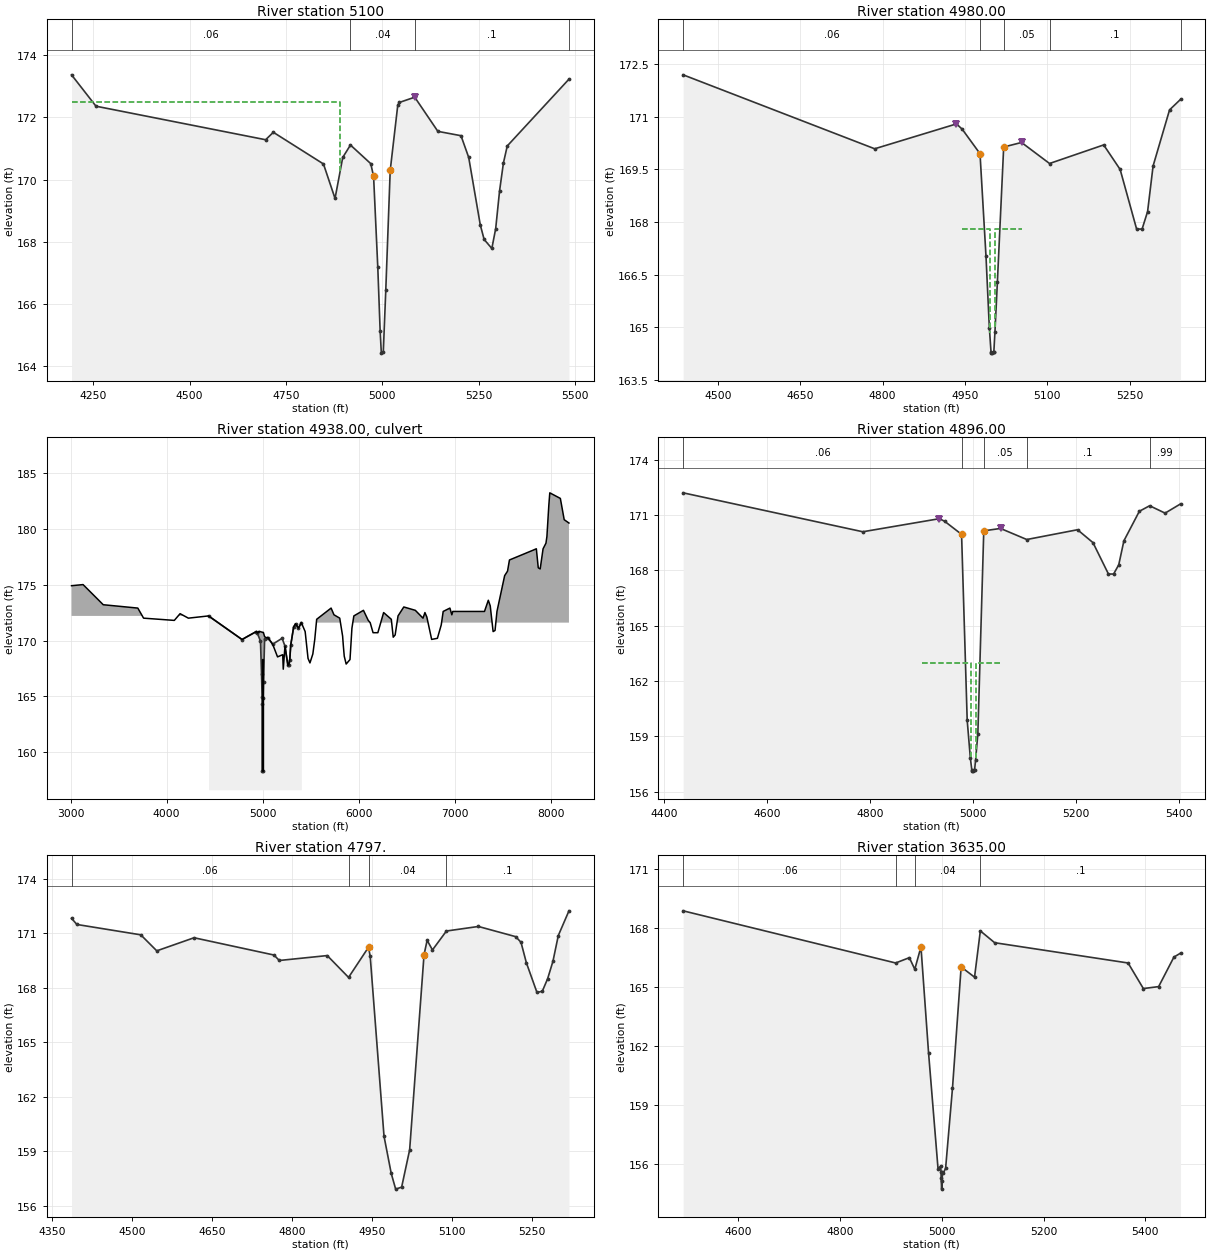
Type RM Length L Ch R = 1 ,5100    ,120,120,120
BEGIN DESCRIPTION:
Upstream Section of Bridge/Culvert/Weir
END DESCRIPTION:
XS GIS Cut Line= 5
 3002985.096849413927224.8507254       3002937.2     13927183.26
      3002321.44     13926844.72      3002247.78      13926804.3
 3001808.167916513926822.1389854
#Sta/Elev= 30
    4194  173.37  4257.4  172.36  4697.4  171.28  4717.4  171.52  4847.4   170.5
  4877.4  169.39  4897.4  170.71  4917.4  171.11  4970.1  170.51  4977.4   170.1
  4988.3  167.17  4994.4  165.13  4997.5  164.41  5002.6  164.45    5009  166.43
  5020.5  170.29  5040.1  172.39  5044.1  172.48  5084.1  172.65  5144.1  171.55
  5204.1  171.41  5224.1  170.71  5254.1  168.54  5264.1  168.07  5284.1  167.78
  5294.1  168.42  5304.1  169.63  5314.1  170.53  5324.1  171.08  5484.1  173.23
#Mann= 4 ,-1 , 0
    4194     .06       0  4917.4     .04       0  5084.1      .1       0
  5484.1     .99       0
Levee=0,,,-1,5084.1,172.65,,
#XS Ineff= 2 , 0
         4889.76  172.51
Permanent Ineff=
       F       F
Bank Sta=4977.4,5020.5
XS Rating Curve= 0
Exp/Cntr=.5,.3

Type RM Length L Ch R = 1 ,4980.00 ,84,84,84
BEGIN DESCRIPTION:
Upstream Section of Bridge/Culvert/Weir
END DESCRIPTION:
XS GIS Cut Line= 4
 3002811.620459913926965.2845459      3002320.89     13926709.88
      3002218.29     13926706.75 3001968.364620813926715.4918807
#Sta/Elev= 25
  4436.7   172.2  4785.6  170.09  4934.5   170.8  4944.9  170.65  4977.4  169.95
  4988.3  167.02  4994.4  164.98  4997.4   164.3  4997.5  164.26  4999.8  164.26
  5002.4   164.3  5002.6   164.3  5004.6  164.87    5009  166.28  5020.5  170.14
    5053  170.27    5104  169.67  5202.6   170.2  5232.6   169.5  5262.6   167.8
  5272.6   167.8  5282.6   168.3  5292.6   169.6  5322.6   171.2  5342.6   171.5
#Mann= 5 ,-1 , 0
  4436.7     .06       0  4977.4     .04       0  5020.5     .05       0
    5104      .1       0  5342.6     .99       0
Levee=-1,4934.5,170.8,-1,5053,170.27,,
#XS Ineff= 2 ,-1
    4945    4995   167.8    5005    5053   167.8
Permanent Ineff=
       F       F
Bank Sta=4977.4,5020.5
XS Rating Curve= 0
Exp/Cntr=.5,.3

Type RM Length L Ch R = 2 ,4938.00 ,,,
BEGIN DESCRIPTION:
OAK ORCHARD / EDWORTHY
Structure ID: K159-01-00-S4
Raised the n-value of the culvert in an effort to bump the 100-year WSEL over the weir.  This was deemed necessary because of the restriction on the upstream side of the culvert. -KHH
END DESCRIPTION:
Bridge Culvert--1,0,-1,-1, 0
Deck Dist Width WeirC Skew NumUp NumDn MinLoCord MaxHiCord MaxSubmerge Is_Ogee
10,64,2.6,0, 115, 115, , , .95, 0, ,,,
  3010.4  3130.4  3300.9  3340.4  3700.4  3760.4  4080.4  4140.4  4226.7  4436.7
  4785.6  4846.1  4846.4  4899.3  4934.5  4944.9    4952 4962.09  4962.2 4962.31
  4969.2  4970.9  4977.4  4988.3  4994.4  4997.4  4997.5  4999.8  5002.4  5002.6
  5004.6  5008.2    5009  5020.5 5043.29  5043.4 5043.51    5053  5062.5    5104
  5108.7    5155    5161    5199  5209.1  5214.6  5232.6  5262.6  5272.6  5282.6
  5292.6  5322.6  5342.6  5372.6  5402.6  5442.6  5472.6  5492.6  5522.6  5542.6
  5562.6  5712.6  5742.6  5802.6  5832.6  5839.5  5849.5  5869.5  5909.5  5929.5
  5949.5  6049.5  6099.5  6119.5  6149.5  6199.5  6259.5  6339.5  6359.5  6379.5
  6409.5  6469.5  6589.5  6669.5  6689.5  6709.5  6759.5  6819.5  6859.5  6879.5
  6949.5  6969.5  6979.5  7009.5  7309.5  7349.5  7369.5  7399.5  7419.5  7439.5
  7519.5  7549.5  7569.5  7814.3  7849.5  7869.5  7889.5  7919.5  7949.5  7959.5
  7979.5  7989.5  8099.5  8139.5    8189
   174.9     175  173.54   173.2   172.9     172   171.8   172.4     172   172.2
  170.09  170.39  170.39  170.64  170.81  170.66  170.76  170.73  170.83  170.83
  170.81  170.81  170.79  170.76  170.75  170.74  170.74  170.73  170.73  170.72
  170.72  170.71  170.69  170.34  170.24  170.24  170.24  170.28  170.17  169.68
  169.57  168.54  168.56   168.7  168.73  167.44   169.5   167.8   167.8   168.3
   169.6   171.2   171.5   171.1   171.6   170.8   168.4     168   168.8   170.1
   171.9   172.9   172.3     172   170.4   169.6   168.6   167.9   168.3   171.1
   172.2   172.7   171.8   171.6   170.7   170.7   172.5   171.9   170.3   170.5
   172.2     173   172.7     172   172.5   172.1   170.1   170.2   171.4   172.6
   172.9   172.3   172.6   172.6   172.6   173.6   173.1   170.8   170.9   172.6
   175.8   176.2   177.2  178.07   178.2   176.5   176.4   178.2   178.7   179.3
   182.1   183.2   182.7   180.8   180.5
                                                                                
                                                                                
                                                                                
                                                                                
                                                                                
                                                                                
                                                                                
                                                                                
                                                                                
                                                                                
                                                                                
                                        
  3010.4  3130.4  3300.9  3340.4  3700.4  3760.4  4080.4  4140.4  4226.7  4436.7
  4785.6  4846.1  4846.4  4899.3  4934.5  4944.9    4952 4962.09  4962.2 4962.31
  4969.2  4970.9  4977.4  4988.3  4994.4  4997.4  4997.5  4999.8  5002.4  5002.6
  5004.6  5008.2    5009  5020.5 5043.29  5043.4 5043.51    5053  5062.5    5104
  5108.7    5155    5161    5199  5209.1  5214.6  5232.6  5262.6  5272.6  5282.6
  5292.6  5322.6  5342.6  5372.6  5402.6  5442.6  5472.6  5492.6  5522.6  5542.6
  5562.6  5712.6  5742.6  5802.6  5832.6  5839.5  5849.5  5869.5  5909.5  5929.5
  5949.5  6049.5  6099.5  6119.5  6149.5  6199.5  6259.5  6339.5  6359.5  6379.5
  6409.5  6469.5  6589.5  6669.5  6689.5  6709.5  6759.5  6819.5  6859.5  6879.5
  6949.5  6969.5  6979.5  7009.5  7309.5  7349.5  7369.5  7399.5  7419.5  7439.5
  7519.5  7549.5  7569.5  7814.3  7849.5  7869.5  7889.5  7919.5  7949.5  7959.5
  7979.5  7989.5  8099.5  8139.5    8189
   174.9     175  173.54   173.2   172.9     172   171.8   172.4     172   172.2
  170.09  170.39  170.39  170.64  170.81  170.66  170.76  170.73  170.83  170.83
  170.81  170.81  170.79  170.76  170.75  170.74  170.74  170.73  170.73  170.72
  170.72  170.71  170.69  170.34  170.24  170.24  170.24  170.28  170.17  169.68
  169.57  168.54  168.56   168.7  168.73  167.44   169.5   167.8   167.8   168.3
   169.6   171.2   171.5   171.1   171.6   170.8   168.4     168   168.8   170.1
   171.9   172.9   172.3     172   170.4   169.6   168.6   167.9   168.3   171.1
   172.2   172.7   171.8   171.6   170.7   170.7   172.5   171.9   170.3   170.5
   172.2     173   172.7     172   172.5   172.1   170.1   170.2   171.4   172.6
   172.9   172.3   172.6   172.6   172.6   173.6   173.1   170.8   170.9   172.6
   175.8   176.2   177.2  178.07   178.2   176.5   176.4   178.2   178.7   179.3
   182.1   183.2   182.7   180.8   180.5
                                                                                
                                                                                
                                                                                
                                                                                
                                                                                
                                                                                
                                                                                
                                                                                
                                                                                
                                                                                
                                                                                
                                        
BR Coef= 1 , 1 , 1 ,1.25, 0 ,,,.8,0,2,0,167
WSPro=,,,, 1 ,,,, 0 ,,,, 0 ,,,,-1 ,-1 ,-1 , 0 , 0 , 0 , 0 , 0
Culvert=2,10,10,64,.02,.5,1,10,2,158.33,5000,158.33,5000,Culvert #1  , 0 ,10
Culvert Bottom n=.02
BR U #Sta/Elev= 25
  4436.7   172.2  4785.6  170.09  4934.5   170.8  4944.9  170.65  4977.4  169.95
  4988.3  167.02  4994.4  164.98 4994.99   164.3    4995  158.33    5005  158.33
 5005.01  164.87    5009  166.28  5020.5  170.14    5053  170.27    5104  169.67
  5202.6   170.2  5232.6   169.5  5262.6   167.8  5272.6   167.8  5282.6   168.3
  5292.6   169.6  5322.6   171.2  5342.6   171.5  5372.6   171.1  5402.6   171.6
BR U #Mann= 5
  4436.7     .06  4977.4     .04  5020.5     .05    5104      .1  5342.6     .99
BC Design=,, 0 ,, 0 ,,,,,,
BC HTab HWMax=183.2

Type RM Length L Ch R = 1 ,4896.00 ,97,99,99
BEGIN DESCRIPTION:
Downstream Section of Bridge/Culvert/Weir
END DESCRIPTION:
XS GIS Cut Line= 4
 3002819.993768813926882.4439473      3002327.18     13926625.96
      3002223.28     13926622.79 3001910.120185713926633.7436245
#Sta/Elev= 27
  4436.7   172.2  4785.6  170.09  4934.5   170.8  4944.9  170.65  4977.4  169.95
  4988.3  159.88  4994.4  157.84  4997.4  157.16  4997.5  157.12  4999.8  157.12
  5002.4  157.16  5002.6  157.16  5004.6  157.73    5009  159.14  5020.5  170.14
    5053  170.27    5104  169.67  5202.6   170.2  5232.6   169.5  5262.6   167.8
  5272.6   167.8  5282.6   168.3  5292.6   169.6  5322.6   171.2  5342.6   171.5
  5372.6   171.1  5402.6   171.6
#Mann= 5 ,-1 , 0
  4436.7     .06       0  4977.4     .05       0  5020.5     .05       0
    5104      .1       0  5342.6     .99       0
Levee=-1,4934.5,170.8,-1,5053,170.3,,
#XS Ineff= 2 ,-1
    4900    4995     163    5005    5052     163
Permanent Ineff=
       F       F
Bank Sta=4977.4,5020.5
XS Rating Curve= 0
Exp/Cntr=.5,.3

Type RM Length L Ch R = 1 ,4797.   ,1162,1162,1162
XS GIS Cut Line= 4
 3002871.2214251 13926785.901294      3002376.61     13926528.63
      3002230.46     13926524.46 3002000.657149613926532.4979858
#Sta/Elev= 30
  4386.5  171.82  4396.5  171.48  4516.5  170.91  4546.5  170.03  4616.5  170.75
  4766.5   169.8  4776.5   169.5  4866.5  169.77  4906.5  168.57    4944  170.23
4947.156  169.72 4973.05  159.844986.558   157.84994.918  156.935006.138  157.04
5021.164  159.09 5048.16  169.81    5054  170.61    5064  170.08  5090.2  171.12
  5150.2  171.37  5220.2  170.81  5230.2   170.5  5240.2  169.38  5260.2  167.74
  5270.2  167.81  5280.2   168.5  5290.2  169.46  5300.2  170.87  5320.2  172.23
#Mann= 4 ,-1 , 0
  4386.5     .06       0  4906.5     .12       0    4944     .04       0
  5090.2      .1       0
Bank Sta=4944,5048.16
XS Rating Curve= 0
Exp/Cntr=.3,.1

Type RM Length L Ch R = 1 ,3635.00 ,573,573,573
BEGIN DESCRIPTION:
Cross Section K159-01-00-X03
END DESCRIPTION:
XS GIS Cut Line= 5
 3002827.451640913925566.2170978      3002409.83     13925364.59
       3002299.9     13925366.28      3001897.34     13925384.75
 3001897.330815213925384.7579584
#Sta/Elev= 25
  4492.3  168.85  4909.6   166.2  4936.5  166.47  4947.2  165.88  4959.3  167.02
  4974.2  161.64  4992.8  155.75  4997.9  155.88  4998.7   155.6  4998.9   155.3
  4999.9  154.71    5001  155.12  5001.3  155.57  5003.2  155.52  5007.7  155.77
  5021.2  159.84  5038.2     166  5064.5  165.48  5075.9  167.83    5104  167.23
    5366   166.2    5396   164.9    5426     165    5456   166.5    5469   166.7
#Mann= 4 ,-1 , 0
  4492.3     .06       0  4909.6     .12       0  4947.2     .04       0
  5075.9      .1       0
Bank Sta=4959.3,5038.2
XS Rating Curve= 0
Exp/Cntr=.3,.1

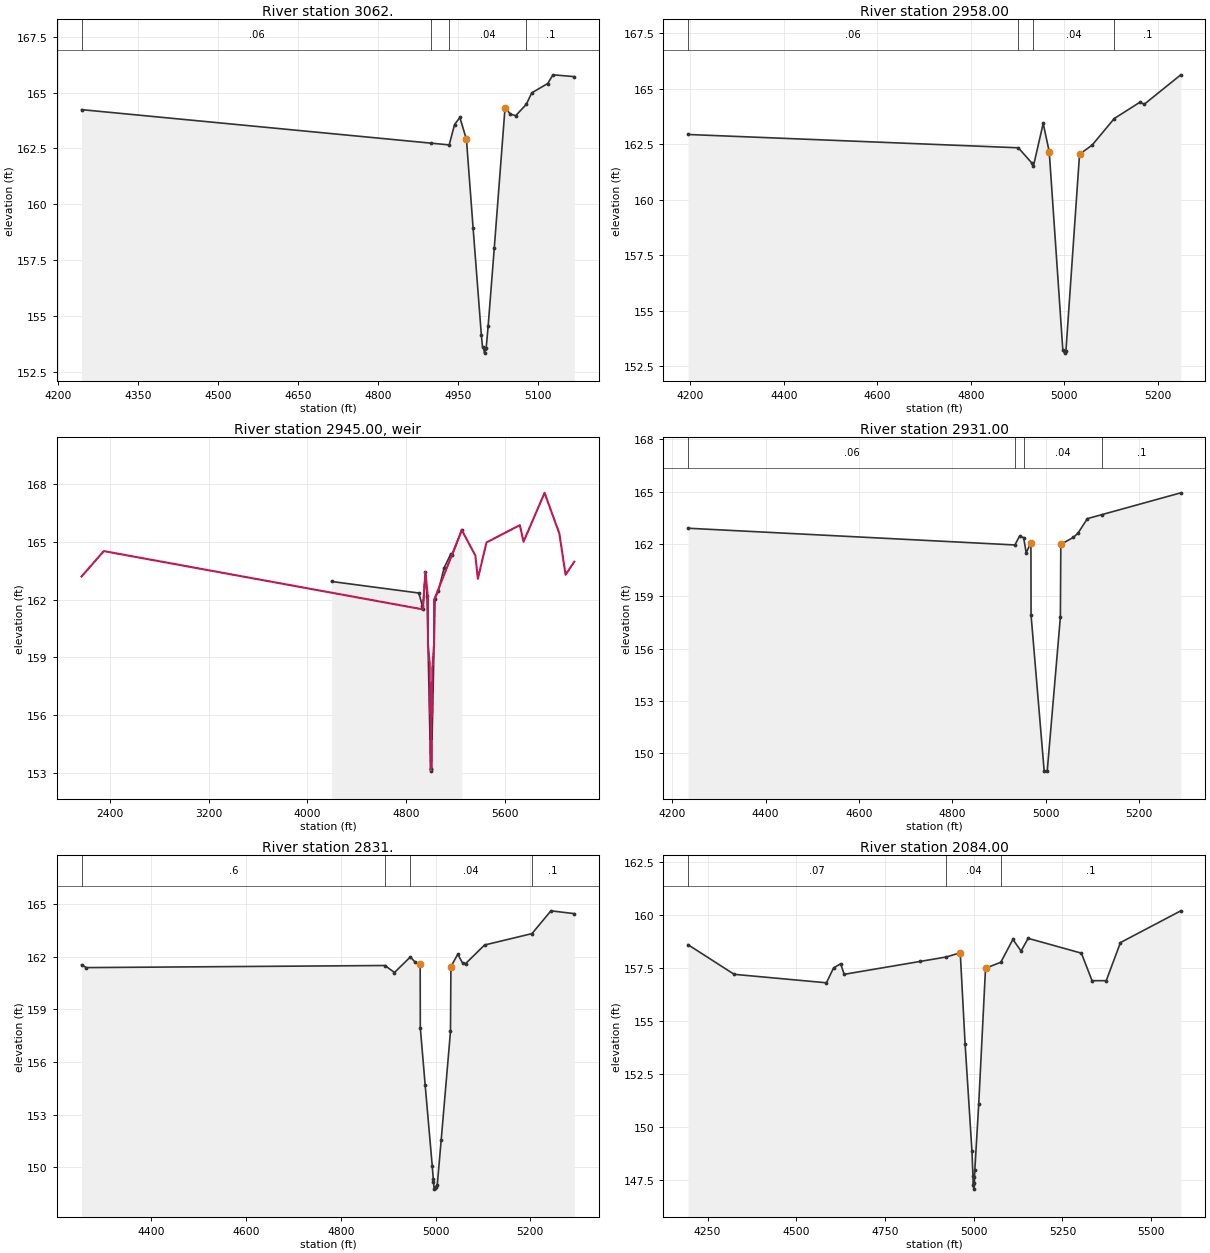
Type RM Length L Ch R = 1 ,3062.   ,104,104,104
XS GIS Cut Line= 4
      3003117.31     13924974.89      3002420.84     13924794.11
      3002345.65     13924791.16 3002241.666416113924869.1912422
#Sta/Elev= 23
    4244  164.24    4900 162.738    4934  162.66    4944  163.57    4954  163.89
 4966.33  162.91  4978.8  158.95 4994.38  154.13 4996.49  153.61 4998.65  153.55
 5000.32  153.33 5001.53   153.5 5003.31  153.54 5007.04  154.53 5018.66  158.06
  5038.8  164.33  5048.8  164.04  5058.8  163.97  5078.8  164.48  5088.8  164.99
  5118.8  165.41  5128.8   165.8  5168.8  165.72
#Mann= 4 ,-1 , 0
    4244     .06       0    4900     .12       0    4934     .04       0
  5078.8      .1       0
Bank Sta=4966.33,5038.8
XS Rating Curve= 0
Exp/Cntr=.7,.5

Type RM Length L Ch R = 1 ,2958.00 ,27,27,27
BEGIN DESCRIPTION:
Upstream Section of Bridge/Culvert/Weir
END DESCRIPTION:
XS GIS Cut Line= 4
 3003168.1380247 13924883.605035       3002424.3     13924690.53
       3002349.1     13924687.58  3002181.09321113924813.6605223
#Sta/Elev= 15
 4195.12  162.94  4901.5  162.34  4930.1  161.66  4933.7  161.51  4954.7  163.44
  4967.6  162.16  4996.7  153.21  5000.4  153.08  5003.3  153.18  5032.4  162.05
  5059.3  162.46  5106.7  163.66  5161.2  164.39  5171.2  164.31  5248.9  165.63
#Mann= 4 ,-1 , 0
 4195.12     .06       0  4901.5     .12       0  4933.7     .04       0
  5106.7      .1       0
#XS Ineff= 2 , 0
       0 4967.51  162.16  5032.4       0  162.05
Permanent Ineff=
       F       F
Bank Sta=4967.6,5032.4
XS Rating Curve= 0
Exp/Cntr=.7,.5

Type RM Length L Ch R = 5 ,2945.00 ,,,
BEGIN DESCRIPTION:
SHEET PILING DROP STRUCTURE 570' FROM ASPENWILDE
Structure ID: K159-01-00-S3
END DESCRIPTION:
IW Pilot Flow=0
#Inline Weir SE= 30
  2171.5   163.2  2351.5  164.52  4933.7  161.49  4954.7  163.42  4975.5  162.08
  4975.7  159.65  4989.7  158.64  4989.9  157.59  4991.2  157.62  4991.4  156.13
  4996.8   156.1  4997.1  153.16  5000.4  153.15  5003.2  153.17  5003.5  155.98
    5009  155.97  5009.2  157.59  5010.8  158.45  5024.7   159.7    5025  161.98
  5248.9  165.61  5358.9  164.29  5378.9  163.08  5448.9  164.97  5718.9  165.87
  5748.9  165.01  5918.9  167.55  6038.9  165.43  6088.9  163.29  6159.7  163.97
IW Dist,WD,Coef,Skew,MaxSub,Min_El,Is_Ogee,SpillHt,DesHd
10,1,3,0,.95,, 0 ,,,0,0,

Type RM Length L Ch R = 1 ,2931.00 ,100,100,100
BEGIN DESCRIPTION:
Cross Section FIELD_DS
Located At: SHEET PILING DROP STRUCTURE 570' FROM ASPENWILDE
END DESCRIPTION:
XS GIS Cut Line= 4
 3003137.809929413924818.4892119      3002435.71     13924664.91
      3002319.37     13924657.94 3002135.977789813924779.3830916
#Sta/Elev= 16
    4234  162.91    4934  161.95    4944  162.46  4952.7  162.37 4958.19   161.5
  4968.3  162.08  4968.6  157.93  4996.7  148.98  5003.3  149.01  5031.4  157.82
  5032.3  161.98  5059.3  162.39  5069.2  162.63  5089.2  163.46    5120 163.688
  5289.2  164.94
#Mann= 4 ,-1 , 0
    4234     .06       0    4934     .12       0  4952.7     .04       0
    5120      .1       0
#XS Ineff= 2 , 0
          4968.3  162.08  5032.3          161.98
Permanent Ineff=
       F       F
Bank Sta=4968.3,5032.3
XS Rating Curve= 0
Exp/Cntr=.7,.5

Type RM Length L Ch R = 1 ,2831.   ,747,747,747
XS GIS Cut Line= 4
      3003122.82     13924714.08      3002445.25     13924565.87
      3002328.92      13924558.9      3002137.75     13924685.49
#Sta/Elev= 27
  4253.3  161.55  4263.3  161.39  4893.3  161.51  4913.3  161.11  4946.9     162
  4956.9   161.7 4967.56  161.62 4967.87  157.95 4978.13  154.68 4992.96  150.09
 4995.19  149.34 4995.66  149.17 4997.12  148.75 4998.95  148.79 4999.06  148.83
 5000.02  148.87 5003.67     149 5011.82  151.53 5031.51  157.75 5032.41  161.45
  5046.9  162.15  5056.9  161.66  5063.4  161.62  5103.4  162.68  5203.4  163.33
  5243.4  164.63  5292.7  164.47
#Mann= 4 ,-1 , 0
  4253.3      .6       0  4893.3     .12       0  4946.9     .04       0
  5203.4      .1       0
Bank Sta=4967.56,5032.41
XS Rating Curve= 0
Exp/Cntr=.3,.1

Type RM Length L Ch R = 1 ,2084.00 ,1151,1151,1151
BEGIN DESCRIPTION:
Cross Section K159-01-00-X01
END DESCRIPTION:
XS GIS Cut Line= 4
 3003183.159110713924068.9177905      3002471.93     13923817.92
      3002387.97     13923813.66 3001978.141234513924180.4349018
#Sta/Elev= 29
    4195   158.6    4325   157.2    4585   156.8    4605   157.5    4625   157.7
    4635   157.2  4849.3  157.81  4922.8  158.02    4962  158.22  4975.7   153.9
  4994.9  148.87  4997.8  147.66  4998.4  147.26  5000.3  147.05    5002  147.32
  5002.1  147.63    5003  147.94    5014  151.06  5033.2  157.49  5033.3  157.49
  5076.3  157.77  5110.3  158.85  5133.3   158.3  5153.3   158.9  5303.3   158.2
  5333.3   156.9  5373.3   156.9  5413.3   158.7  5583.3   160.2
#Mann= 3 ,-1 , 0
    4195     .07       0  4922.8     .04       0  5076.3      .1       0
Bank Sta=4962,5033.2
XS Rating Curve= 0
Exp/Cntr=.3,.1

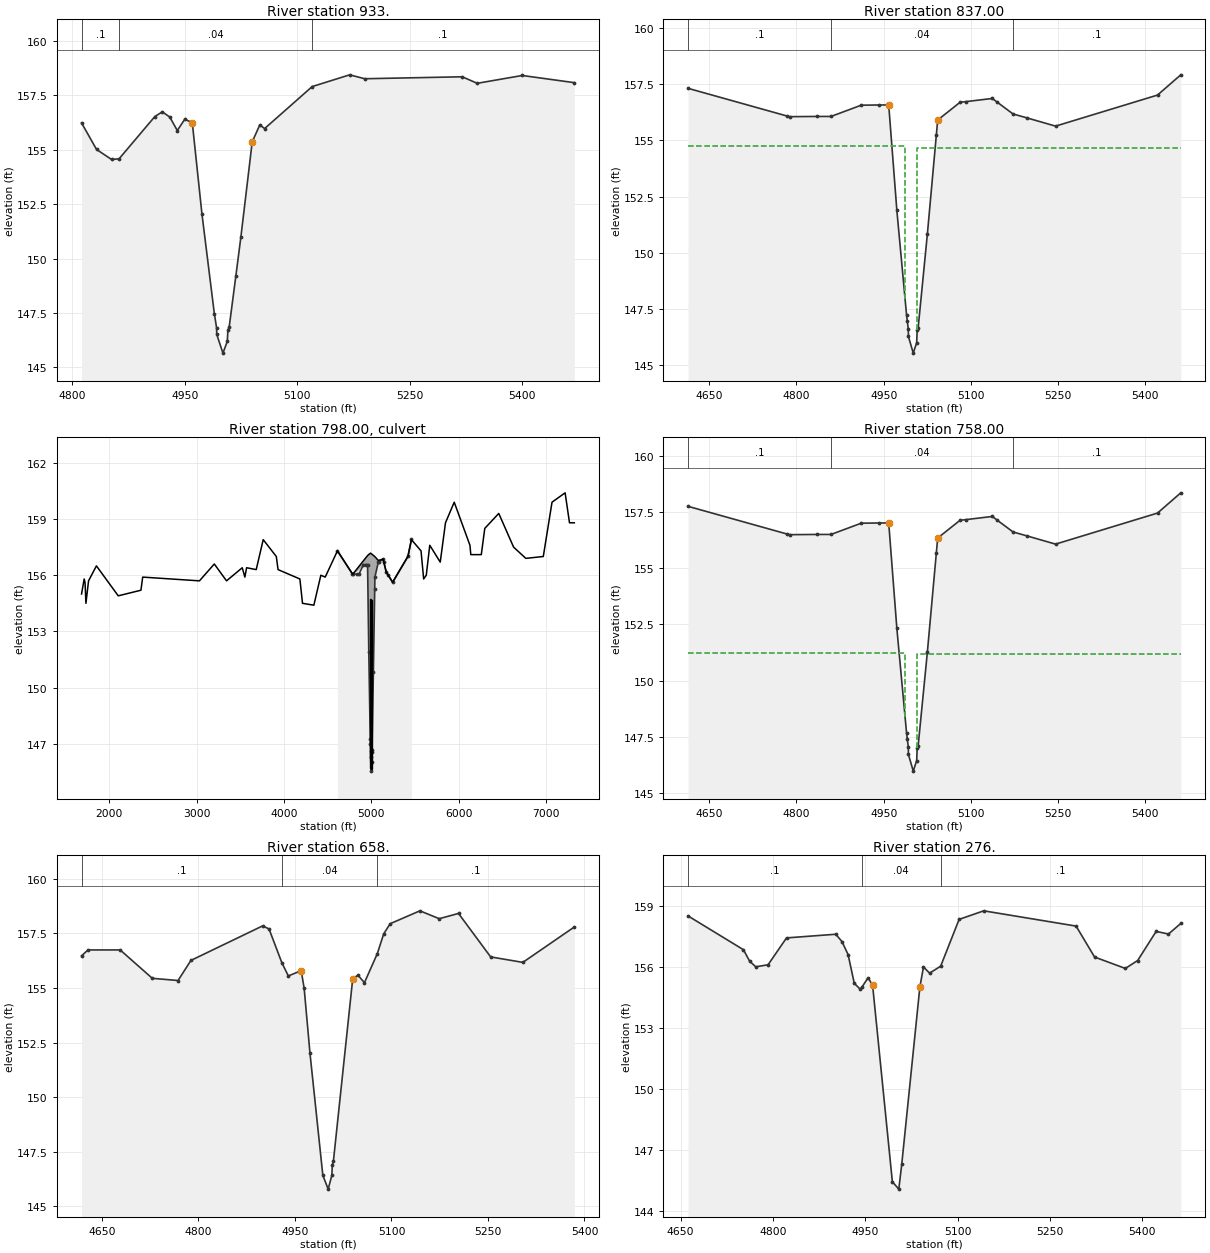
Type RM Length L Ch R = 1 ,933.    ,96,96,96
XS GIS Cut Line= 5
 3002652.678406413922690.0495055      3002557.71     13922667.48
      3002411.32     13922665.04      3002356.43     13922696.76
      3002191.94     13923004.98
#Sta/Elev= 30
  4812.4  156.24  4832.4  155.02  4852.4  154.56  4862.4  154.59    4910  156.53
    4920  156.75    4930  156.51    4940  155.89    4950  156.41    4960  156.25
 4972.85  152.06 4989.44  147.46 4992.41  146.82 4992.61  146.52 5000.85  145.66
 5006.66   146.2 5007.44  146.71 5009.11  146.84 5018.05   149.2 5024.75  150.99
 5039.89  155.37    5050  156.15  5056.4  155.98  5119.8  157.91  5169.8  158.45
  5189.8  158.27  5319.8  158.36  5339.8  158.06  5399.8  158.42  5469.2  158.09
#Mann= 3 ,-1 , 0
  4812.4      .1       0  4862.4     .04       0  5119.8      .1       0
Bank Sta=4960,5039.89
XS Rating Curve= 0
Exp/Cntr=.5,.3

Type RM Length L Ch R = 1 ,837.00  ,79,79,79
BEGIN DESCRIPTION:
Upstream Section of Bridge/Culvert/Weir
END DESCRIPTION:
XS GIS Cut Line= 5
 3002849.609983413922637.9296949      3002569.79     13922571.43
      3002423.39     13922568.99      3002368.51     13922600.71
 3002203.731966313922909.4515842
#Sta/Elev= 29
  4613.6  157.31  4783.7  156.08  4788.5  156.05  4835.8  156.06  4859.5  156.06
  4911.4  156.56  4941.4  156.57  4958.7  156.57  4972.7  151.88  4989.4  147.23
  4990.6  146.98  4992.4   146.6  4992.6  146.28  5000.9  145.54  5006.8  146.01
  5007.6  146.55  5009.3  146.66  5025.2  150.84  5040.6  155.24  5042.9   155.9
  5081.4  156.69  5091.9  156.72  5136.9  156.86    5145   156.7  5172.5  156.17
  5197.2  155.99  5245.6  155.63  5420.9  157.01  5460.9  157.91
#Mann= 3 ,-1 , 0
  4613.6      .1       0  4859.5     .04       0  5172.5      .1       0
#XS Ineff= 2 , 0
       0  4986.9  154.73  5007.7       0  154.67
Permanent Ineff=
       F       F
Bank Sta=4958.7,5042.9
XS Rating Curve= 0
Exp/Cntr=.5,.3

Type RM Length L Ch R = 2 ,798.00  ,,,
BEGIN DESCRIPTION:
CHESTNUT FALLS
Structure ID: K159-01-00-S2
END DESCRIPTION:
Bridge Culvert--1,0,-1,-1, 0
Deck Dist Width WeirC Skew NumUp NumDn MinLoCord MaxHiCord MaxSubmerge Is_Ogee
10,62,2.6,0, 60, 60, , , .95, 0, ,,,
  1683.5  1713.6  1723.6  1733.6  1763.6  1853.6  2103.6  2363.6  2383.6  3033.6
  3203.6  3343.6  3523.6  3553.6  3573.6  3683.6  3763.6  3913.6  3933.6  4183.6
  4213.6  4343.6  4423.6  4473.6  4613.6  4788.5  4958.7  4972.7  4992.6  5000.9
  5006.8  5007.6  5009.3  5025.2  5042.9  5081.4  5136.9  5172.5  5245.6  5420.9
  5460.9  5570.9  5600.9  5630.9  5670.9  5790.9  5850.9  5950.9  6130.9  6140.9
  6260.9  6300.9  6460.9  6630.9  6770.9  6970.9  7070.9  7220.9  7270.9  7326.1
     155   155.8   155.6   154.5   155.7   156.5   154.9   155.2   155.9   155.7
   156.6   155.7   156.4   155.9   156.4   156.3   157.9     157   156.3   155.8
   154.5   154.4     156   155.9   157.3  156.05  157.05  157.11  157.18  157.15
  157.13  157.13  157.12  157.06  156.99  156.79  156.86  156.17  155.62     157
   157.9   157.3   155.8     156   157.6   156.7   158.8   159.9   157.6   157.1
   157.1   158.5   159.3   157.5   156.9     157   159.9   160.4   158.8   158.8
     155   155.8   155.6   154.5   155.7   156.5   154.9   155.2   155.9   155.7
   156.6   155.7   156.4   155.9   156.4   156.3   157.9     157   156.3   155.8
   154.5   154.4     156   155.9   157.3  156.04  156.56  151.87  146.27  145.53
     146  146.54  146.65  150.83  155.89  156.68  156.85  156.16  155.62     157
   157.9   157.3   155.8     156   157.6   156.7   158.8   159.9   157.6   157.1
   157.1   158.5   159.3   157.5   156.9     157   159.9   160.4   158.8   158.8
  1683.5  1713.6  1723.6  1733.6  1763.6  1853.6  2103.6  2363.6  2383.6  3033.6
  3203.6  3343.6  3523.6  3553.6  3573.6  3683.6  3763.6  3913.6  3933.6  4183.6
  4213.6  4343.6  4423.6  4473.6  4613.6  4788.5  4958.7  4972.7  4992.6  5000.9
  5006.8  5007.6  5009.3  5025.2  5042.9  5081.4  5136.9  5172.5  5245.6  5420.9
  5460.9  5570.9  5600.9  5630.9  5670.9  5790.9  5850.9  5950.9  6130.9  6140.9
  6260.9  6300.9  6460.9  6630.9  6770.9  6970.9  7070.9  7220.9  7270.9  7326.1
     155   155.8   155.6   154.5   155.7   156.5   154.9   155.2   155.9   155.7
   156.6   155.7   156.4   155.9   156.4   156.3   157.9     157   156.3   155.8
   154.5   154.4     156   155.9   157.3  156.05  157.05  157.11  157.18  157.15
  157.13  157.13  157.12  157.06  156.99  156.79  156.86  156.17  155.62     157
   157.9   157.3   155.8     156   157.6   156.7   158.8   159.9   157.6   157.1
   157.1   158.5   159.3   157.5   156.9     157   159.9   160.4   158.8   158.8
     155   155.8   155.6   154.5   155.7   156.5   154.9   155.2   155.9   155.7
   156.6   155.7   156.4   155.9   156.4   156.3   157.9     157   156.3   155.8
   154.5   154.4     156   155.9   157.3  156.04  156.56  151.87  146.27  145.53
     146  146.54  146.65  150.83  155.89  156.68  156.85  156.16  155.62     157
   157.9   157.3   155.8     156   157.6   156.7   158.8   159.9   157.6   157.1
   157.1   158.5   159.3   157.5   156.9     157   159.9   160.4   158.8   158.8
BR Coef= 1 , 1 , 0 ,1.25, 0 ,,,.8,-1,2,0,
WSPro=,,,, 1 ,,,, 0 ,,,, 0 ,,,,-1 ,-1 ,-1 , 0 , 0 , 0 , 0 , 0
Culvert=2,9,9,62,.015,.4,1,8,1,145.73,4991.4,145.53,4991.4,Culvert #1  , 0 ,10
Culvert Bottom n=.015
Culvert=2,9,9,62,.015,.4,1,8,1,145.67,5002.2,145.56,5002.2,Culvert #2  , 0 ,10
Culvert Bottom n=.015
BC Design=,, 0 ,, 0 ,,,,,,
BC HTab HWMax=160.41

Type RM Length L Ch R = 1 ,758.00  ,100,100,100
BEGIN DESCRIPTION:
Downstream Section of Bridge/Culvert/Weir
END DESCRIPTION:
XS GIS Cut Line= 5
      3002847.83      13922557.6      3002574.11     13922492.63
      3002425.78     13922490.16      3002368.46     13922523.28
 3002203.006851513922833.2888544
#Sta/Elev= 29
  4613.6  157.75  4783.7  156.52  4788.5  156.49  4835.8   156.5  4859.5   156.5
  4911.4     157  4941.4  157.01  4958.7  157.01  4972.7  152.32  4989.4  147.67
  4990.6  147.42  4992.4  147.04  4992.6  146.72  5000.9  145.98  5006.8  146.45
  5007.6  146.99  5009.3   147.1  5025.2  151.28  5040.6  155.68  5042.9  156.34
  5081.4  157.13  5091.9  157.16  5136.9   157.3    5145  157.14  5172.5  156.61
  5197.2  156.43  5245.6  156.07  5420.9  157.45  5460.9  158.35
#Mann= 3 ,-1 , 0
  4613.6      .1       0  4859.5     .04       0  5172.5      .1       0
#XS Ineff= 2 , 0
       0  4986.9  151.23  5007.7       0  151.17
Permanent Ineff=
       F       F
Bank Sta=4958.7,5042.9
XS Rating Curve= 0
Exp/Cntr=.5,.3

Type RM Length L Ch R = 1 ,658.    ,382,382,382
XS GIS Cut Line= 5
      3002852.73     13922457.27      3002579.01     13922392.22
      3002430.68     13922389.75      3002373.36     13922422.87
 3002246.213868813922661.0971869
#Sta/Elev= 30
  4618.3  156.47  4628.3  156.74  4678.3  156.74  4728.3  155.44  4768.3  155.34
  4788.3  156.26  4899.7  157.84  4909.7   157.7  4929.7  156.15  4939.7  155.55
  4959.7  155.79 4964.31  154.98 4973.38     152 4993.32  146.42 5001.64  145.79
 5007.31  146.42 5008.08   146.9 5009.72  147.06 5039.81  155.43    5048  155.58
    5058  155.24    5078  156.57    5088  157.48    5098  157.94  5144.2  158.53
  5174.2  158.17  5204.2  158.41  5254.2  156.42  5304.2  156.17  5384.2  157.79
#Mann= 3 ,-1 , 0
  4618.3      .1       0  4929.7     .04       0    5078      .1       0
Bank Sta=4959.7,5039.81
XS Rating Curve= 0
Exp/Cntr=.3,.1

Type RM Length L Ch R = 1 ,276.    ,98,98,98
XS GIS Cut Line= 4
      3002822.92     13922081.18       3002549.1     13922011.96
      3002421.47     13922004.84 3002237.178398513922348.5622504
#Sta/Elev= 30
  4662.1   158.5  4752.1  156.84  4762.1  156.28  4772.1     156  4792.1   156.1
  4822.1  157.42  4902.1   157.6  4912.1  157.24  4922.1   156.6  4932.1  155.19
  4942.1  154.89  4944.5     155  4954.5  155.46 4961.86   155.1 4993.99  145.44
 5004.47  145.08 5009.28  146.32 5038.66  155.01  5044.5  155.99  5054.5  155.69
  5072.4  156.03  5102.4  158.33  5142.4  158.75  5292.4     158  5322.4  156.48
  5372.4  155.92  5392.4  156.31  5422.4  157.74  5442.4  157.61  5462.4  158.13
#Mann= 3 ,-1 , 0
  4662.1      .1       0  4944.5     .04       0  5072.4      .1       0
Bank Sta=4961.86,5038.66
XS Rating Curve= 0
Exp/Cntr=.7,.5

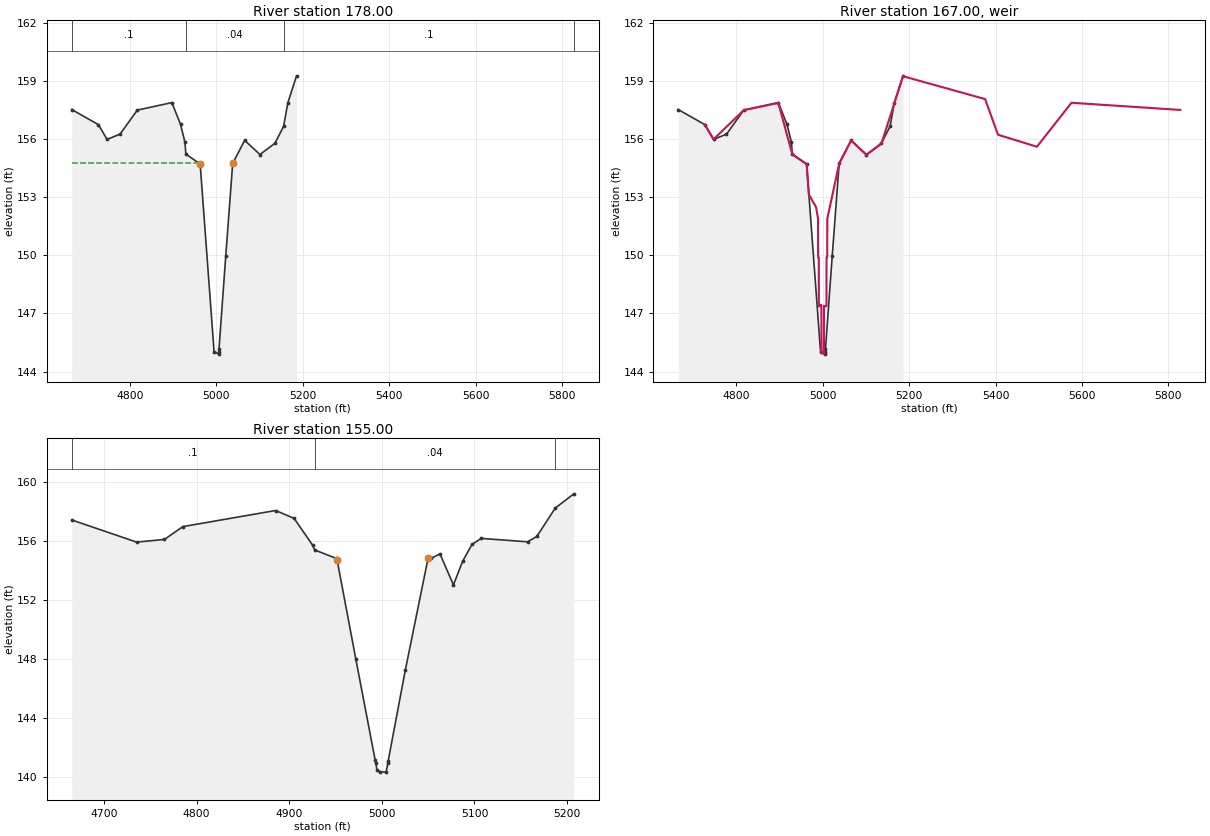
Type RM Length L Ch R = 1 ,178.00  ,23,23,23
BEGIN DESCRIPTION:
Upstream Section of Bridge/Culvert/Weir
END DESCRIPTION:
XS GIS Cut Line= 5
 3002822.918311313921983.6222927       3002763.1      13921968.5
       3002549.1      13921914.4      3002421.47     13921907.28
 3002369.4866729 13922004.234099
#Sta/Elev= 22
  4665.3  157.52    4727  156.74    4747  155.98    4777  156.25    4817  157.49
    4897  157.88    4917  156.76    4927  155.86  4929.5  155.22  4962.5  154.71
  4994.7  145.03  5005.2   144.9  5005.3  145.03  5006.1  145.16  5021.7  149.95
  5037.8  154.74  5065.5  155.93  5100.9   155.2  5135.6  155.78  5155.6  156.65
  5165.6  157.88  5185.6  159.26
#Mann= 4 ,-1 , 0
  4665.3      .1       0  4929.5     .04       0  5155.6      .1       0
  5827.5      .2       0
#XS Ineff= 2 , 0
       0 4962.45  154.74 5037.93       0  154.74
Permanent Ineff=
       F       F
Bank Sta=4962.5,5037.8
XS Rating Curve= 0
Exp/Cntr=.7,.5

Type RM Length L Ch R = 5 ,167.00  ,,,
BEGIN DESCRIPTION:
WIER ON K159-01 AT K159-00
Structure ID: K159-01-00-S1
END DESCRIPTION:
IW Pilot Flow=0
#Inline Weir SE= 30
    4727  156.74    4747  155.98    4817  157.49    4897  157.86  4929.5   155.2
  4962.5   154.7  4967.7  153.14  4984.4  152.48    4989  151.88  4989.2  149.89
  4990.6  149.88  4990.7  147.36  4996.6  147.45  4996.8  144.97  5002.5  144.91
  5002.8  147.39  5008.4  147.37  5008.6  149.91  5010.2   149.9  5010.4  151.89
  5037.8  154.73  5065.5  155.92  5100.9  155.18  5135.6  155.76  5185.6  159.24
  5375.6  158.06  5405.6  156.22  5495.6   155.6  5575.6  157.87  5827.5   157.5
IW Dist,WD,Coef,Skew,MaxSub,Min_El,Is_Ogee,SpillHt,DesHd
10,1,3,0,.95,, 0 ,,,0,0,

Type RM Length L Ch R = 1 ,155.00  ,0,0,0
BEGIN DESCRIPTION:
Cross Section FIELD_DS
Located At: WIER ON K159-01 AT K159-00
END DESCRIPTION:
XS GIS Cut Line= 4
      3002830.22      13921942.9      3002550.96     13921892.82
      3002422.97     13921883.79 3002358.987250613921996.9182962
#Sta/Elev= 30
  4665.3  157.42  4735.3  155.92  4765.3   156.1  4785.3  156.97  4885.3  158.06
  4905.3  157.53  4925.3  155.71  4927.5  155.39  4950.6  154.82  4951.7  154.72
  4971.9  148.01  4992.8  141.16  4993.5  140.98  4994.7   140.5  4998.3  140.36
  5004.6  140.34  5006.6  140.96  5006.8  141.07  5025.4  147.26    5050  154.84
  5053.2  154.82  5062.8  155.12  5077.3  153.02  5087.3  154.63  5097.3  155.76
  5107.3  156.17  5157.3  155.94  5167.3   156.3  5187.3  158.23  5207.3  159.19
#Mann= 3 ,-1 , 0
  4665.3      .1       0  4927.5     .04       0  5187.3      .1       0
#XS Ineff= 2 , 0
         4951.34  154.73    5050          154.84
Permanent Ineff=
       F       F
Bank Sta=4951.7,5050
XS Rating Curve= 0
Exp/Cntr=.7,.5

Chan Stop Cuts=-1